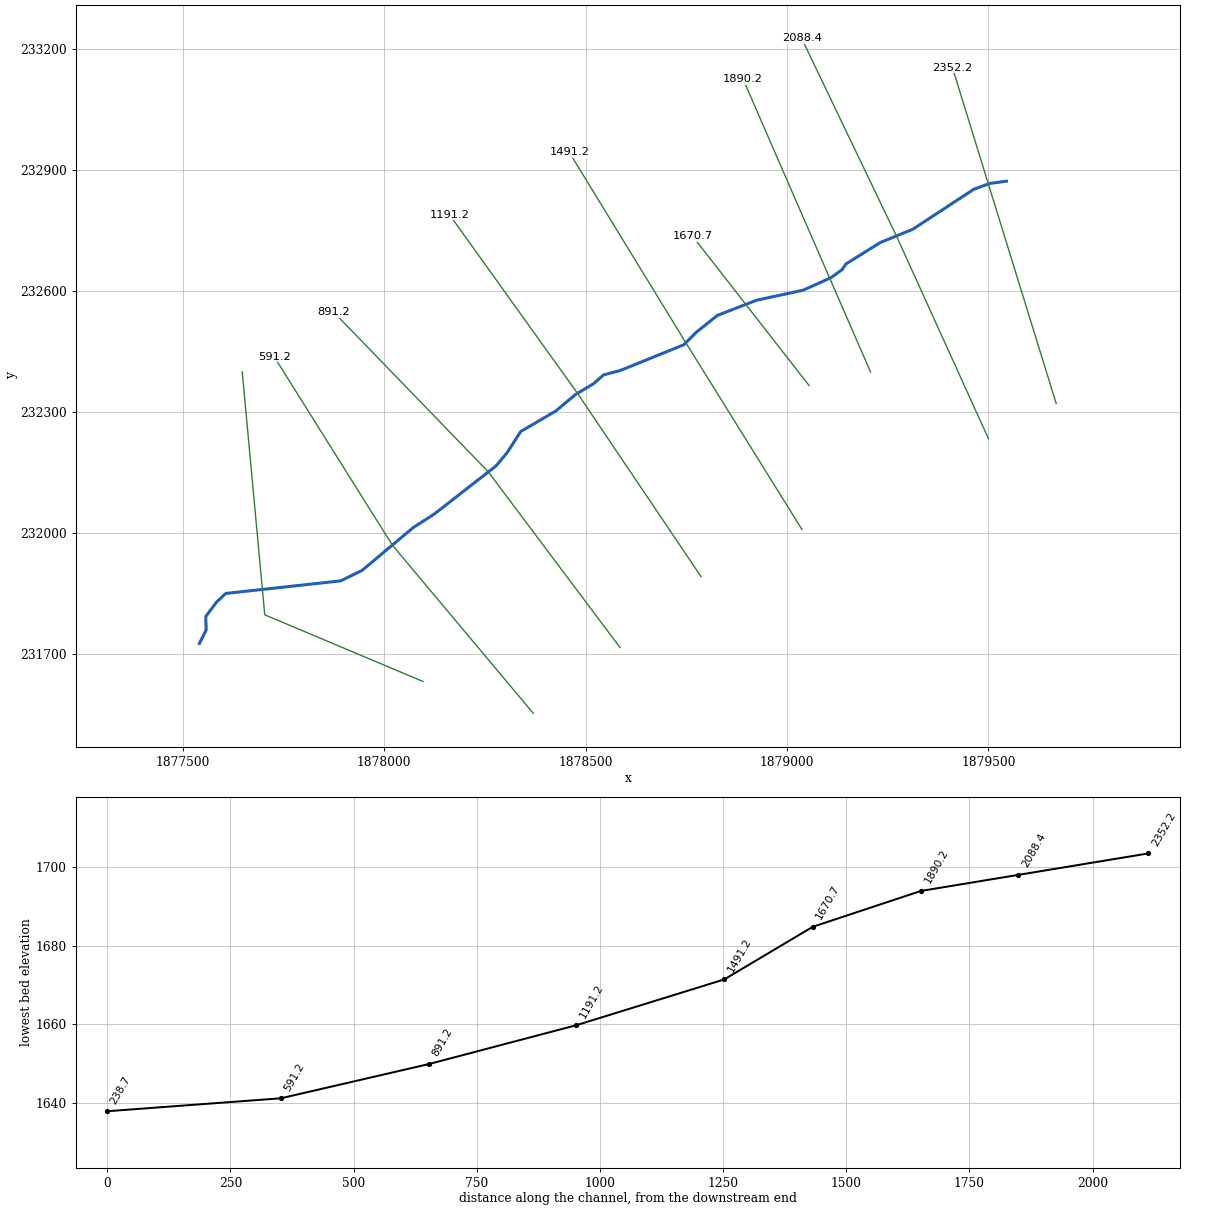
--- BrryBrnch.prj (project) ---

Proj Title=BrryBrnch
Current Plan=p01
Geom File=g01
Flow File=f01
Plan File=p01
DSS Export Rating Curves=0
DSS Export Rating Curve Sorted=0
DSS Export Volume Flow Curves=0
DXF OffsetX=0
DXF OffsetY=0
DXF ScaleX=0
DXF ScaleY=0

--- BrryBrnch.p01 (plan) ---

Plan Title=Floodplain
Program Version=4.00
Geom File=g01
Flow File=f01
K Sum by GR=0
Std Step Tol=0.01
Critical Tol=0.01
Num of Std Step Trials=20
Max Error Tol=0.3
Flow Tol Ratio=0.001
Split Flow NTrial=30
Split Flow Tol=0.02
Split Flow Ratio=0.02
Log Output Level=0
Friction Slope Method=1
Unsteady Friction Slope Method=2
Unsteady Bridges Friction Slope Method=1
Global Log Level=0
CheckData=False
Run HTab=0
Run UNet=0
Run PostProcess=0
UNET Theta=0
UNET Theta Warmup=0
UNET ZTol=0
UNET ZSATol=0
UNET MxIter=0
UNET MaxInSteps=0
UNET DtIC=0
UNET DtMin=0
UNET MaxCRTS=0
UNET WFStab=0
UNET SFStab=0
UNET WFX=0
UNET SFX=0
UNET DSS MLevel=0
UNET DZMax Abort=0
UNET Convert EG Bridges=0
UNET Use Existing IB Tables=0
UNET Froude Limit=0
UNET Froude Power=0
Write IC File=0
Echo Input=False
Echo Output=False
Write Detailed=0

--- BrryBrnch.f01 (steady flow) ---

Flow Title=NFF Regression Equation
Program Version=4.00
Number of Profiles=1
Profile Names=P100yr
River Rch & RM=BrryBrnch,Main      ,2352.2
876.6693
River Rch & RM=BrryBrnch,Main      ,238.7
915.4482
Boundary for River Rch & Prof#=BrryBrnch,Main      ,1
Up Type=0
Dn Type=3
Dn Slope=0.024087

--- BrryBrnch.g01 (geometry) ---

Geom Title=USGS 3m DEM
Program Version=4.00

River Reach=BrryBrnch     ,Main
Reach XY= 30
     1879544.816      232872.993     1879503.653      232867.347
     1879463.209      232852.567     1879312.030      232753.496
     1879231.293      232720.481     1879146.134      232667.381
     1879136.466      232653.163     1879108.956      232633.230
     1879039.936      232602.260     1878924.748      232577.493
     1878827.055      232539.723     1878774.951      232498.044
     1878743.688      232466.783     1878586.077      232402.965
     1878544.372      232391.992     1878519.652      232370.119
     1878475.549      232343.879     1878425.391      232302.027
     1878339.029      232251.638     1878304.716      232198.475
     1878277.361      232165.912     1878123.655      232046.084
     1878072.282      232013.222     1877945.199      231906.718
     1877891.794      231880.669     1877606.533      231849.419
     1877583.086      231827.277     1877557.033      231792.109
     1877557.859      231758.611     1877541.098      231725.242

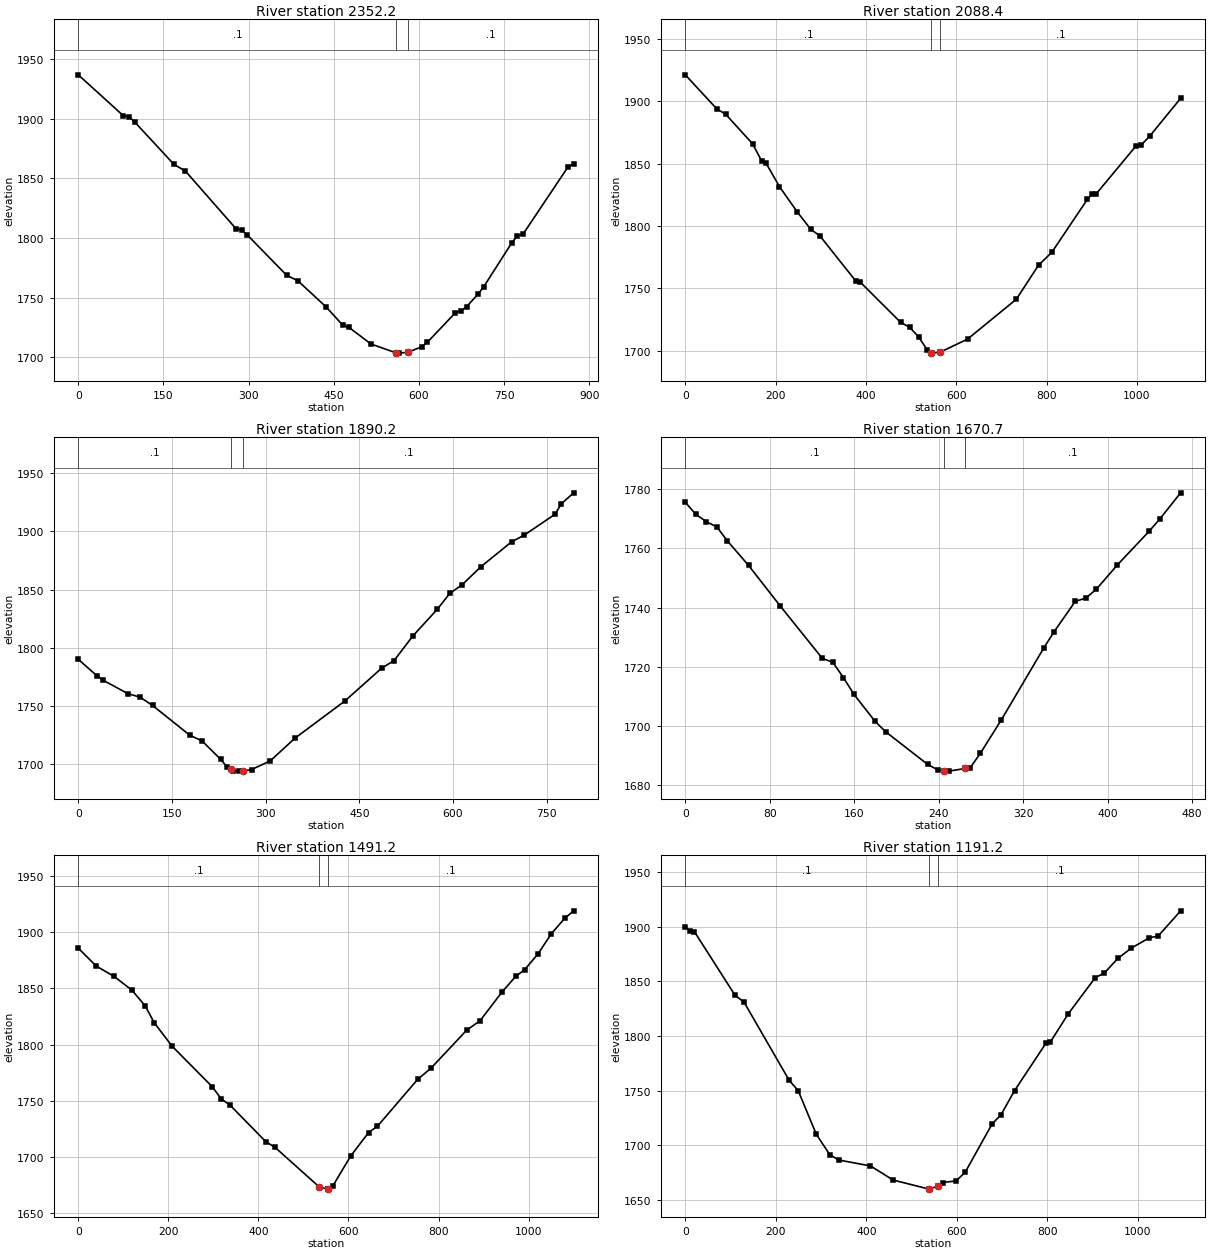
Type RM Length L Ch R = 1 ,2352.2,260.4,263.7,267.4
XS GIS Cut Line= 2
     1879668.131      232321.011     1879410.554      233154.755
#Sta/Elev= 30
       0 1936.83    79.3 1902.56    89.2 1901.76    99.2 1897.35   168.6 1861.69
   188.4 1856.29   277.6 1807.93   287.6 1806.76   297.5 1802.68   366.9 1768.88
   386.7 1764.22   436.3 1742.40   466.1 1726.85   476.0 1725.42   515.6 1711.20
   560.3 1703.68   565.2 1703.56   580.3 1704.27   604.9 1708.86   614.8 1712.62
   664.4 1737.49   674.3 1738.92   684.2 1742.63   704.0 1752.90   714.0 1759.07
   763.6 1796.01   773.5 1801.83   783.4 1803.24   862.7 1859.67   872.6 1862.15
#Mann= 3 , 0 , 0
       0     0.1       0   560.3   0.045       0   580.3     0.1       0
Bank Sta=   560.3,   580.3
Exp/Cntr=0.3,0.1

Type RM Length L Ch R = 1 ,2088.4,198.6,198.1,197.2
XS GIS Cut Line= 3
     1879499.952      232233.726     1879274.185      232731.062
     1879036.191      233227.508
#Sta/Elev= 30
       0 1921.34    69.5 1894.09    89.4 1889.71   149.0 1865.99   168.8 1852.39
   178.8 1850.52   208.5 1831.63   248.3 1811.13   278.1 1797.29   297.9 1792.18
   377.4 1755.98   387.3 1755.07   476.7 1722.78   496.5 1718.84   516.4 1711.24
   536.2 1700.34   544.6 1698.45   546.2 1698.09   564.6 1698.96   624.8 1709.31
   733.0 1741.35   782.1 1768.66   811.6 1779.02   890.3 1821.49   900.1 1825.34
   909.9 1825.92   998.4 1864.54  1008.2 1864.66  1027.9 1872.00  1096.7 1902.53
#Mann= 3 , 0 , 0
       0     0.1       0   544.6   0.045       0   564.6     0.1       0
Bank Sta=   544.6,   564.6
Exp/Cntr=0.3,0.1

Type RM Length L Ch R = 1 ,1890.2,213,219.5,226
XS GIS Cut Line= 2
     1879207.508      232398.675     1878890.783      233126.127
#Sta/Elev= 30
       0 1790.03    29.8 1775.92    39.7 1772.10    79.3 1760.58    99.2 1757.49
   119.0 1750.38   178.5 1724.86   198.4 1719.87   228.1 1704.03   238.0 1697.77
   244.4 1695.57   247.9 1694.36   257.9 1693.98   264.4 1694.20   277.7 1695.36
   307.4 1702.76   347.1 1722.33   426.5 1754.05   486.0 1782.51   505.8 1789.00
   535.6 1809.97   575.2 1833.19   595.1 1846.78   614.9 1854.16   644.6 1869.54
   694.2 1891.11   714.1 1896.74   763.7 1914.77   773.6 1923.70   793.4 1933.14
#Mann= 3 , 0 , 0
       0     0.1       0   244.4   0.045       0   264.4     0.1       0
Bank Sta=   244.4,   264.4
Exp/Cntr=0.3,0.1

Type RM Length L Ch R = 1 ,1670.7,182.4,179.5,176.4
XS GIS Cut Line= 2
     1879054.630      232365.651     1878766.091      232735.676
#Sta/Elev= 30
       0 1775.60    10.0 1771.51    20.0 1769.06    30.0 1767.23    39.9 1762.54
    59.9 1754.30    89.8 1740.64   129.8 1722.90   139.8 1721.56   149.8 1716.40
   159.7 1710.78   179.7 1701.67   189.7 1698.16   229.6 1687.09   239.6 1685.18
   245.3 1684.99   249.6 1684.84   265.3 1685.74   269.6 1685.84   279.5 1690.87
   299.5 1702.22   339.4 1726.34   349.4 1731.93   369.4 1742.16   379.4 1743.25
   389.4 1746.27   409.3 1754.47   439.3 1765.80   449.3 1769.89   469.2 1778.79
#Mann= 3 , 0 , 0
       0     0.1       0   245.3   0.045       0   265.3     0.1       0
Bank Sta=   245.3,   265.3
Exp/Cntr=0.3,0.1

Type RM Length L Ch R = 1 ,1491.2,298.9,300,302
XS GIS Cut Line= 3
     1879036.752      232008.590     1878748.708      232471.802
     1878459.201      232944.827
#Sta/Elev= 30
       0 1885.70    39.7 1869.80    79.3 1860.62   119.0 1848.40   148.8 1834.24
   168.6 1819.35   208.3 1798.54   297.5 1762.45   317.4 1751.69   337.2 1746.03
   416.5 1713.56   436.4 1708.75   535.5 1673.20   555.4 1671.42   555.5 1671.45
   565.3 1674.32   604.9 1700.90   644.5 1721.67   664.3 1727.36   753.4 1768.94
   783.2 1778.98   862.4 1812.76   892.1 1821.18   941.6 1847.05   971.3 1860.61
   991.1 1866.52  1020.8 1880.62  1050.5 1898.59  1080.2 1912.28  1100.0 1918.91
#Mann= 3 , 0 , 0
       0     0.1       0   535.5   0.045       0   555.5     0.1       0
Bank Sta=   535.5,   555.5
Exp/Cntr=0.3,0.1

Type RM Length L Ch R = 1 ,1191.2,298.5,300,303.8
XS GIS Cut Line= 3
     1878786.421      231891.286     1878479.722      232346.362
     1878161.977      232789.774
#Sta/Elev= 30
       0 1900.07    10.0 1895.94    20.0 1895.50   109.8 1837.26   129.7 1830.98
   229.5 1759.32   249.4 1749.92   289.4 1709.95   319.3 1691.23   339.2 1686.38
   409.1 1680.98   459.0 1668.08   538.8 1659.75   558.8 1662.69   568.6 1665.76
   598.4 1667.31   618.2 1675.12   677.7 1719.35   697.6 1727.93   727.3 1749.87
   796.7 1793.31   806.6 1794.55   846.3 1820.40   905.8 1853.45   925.7 1857.52
   955.4 1870.89   985.2 1880.33  1024.9 1889.84  1044.7 1891.45  1094.3 1914.52
#Mann= 3 , 0 , 0
       0     0.1       0   538.8   0.045       0   558.8     0.1       0
Bank Sta=   538.8,   558.8
Exp/Cntr=0.3,0.1

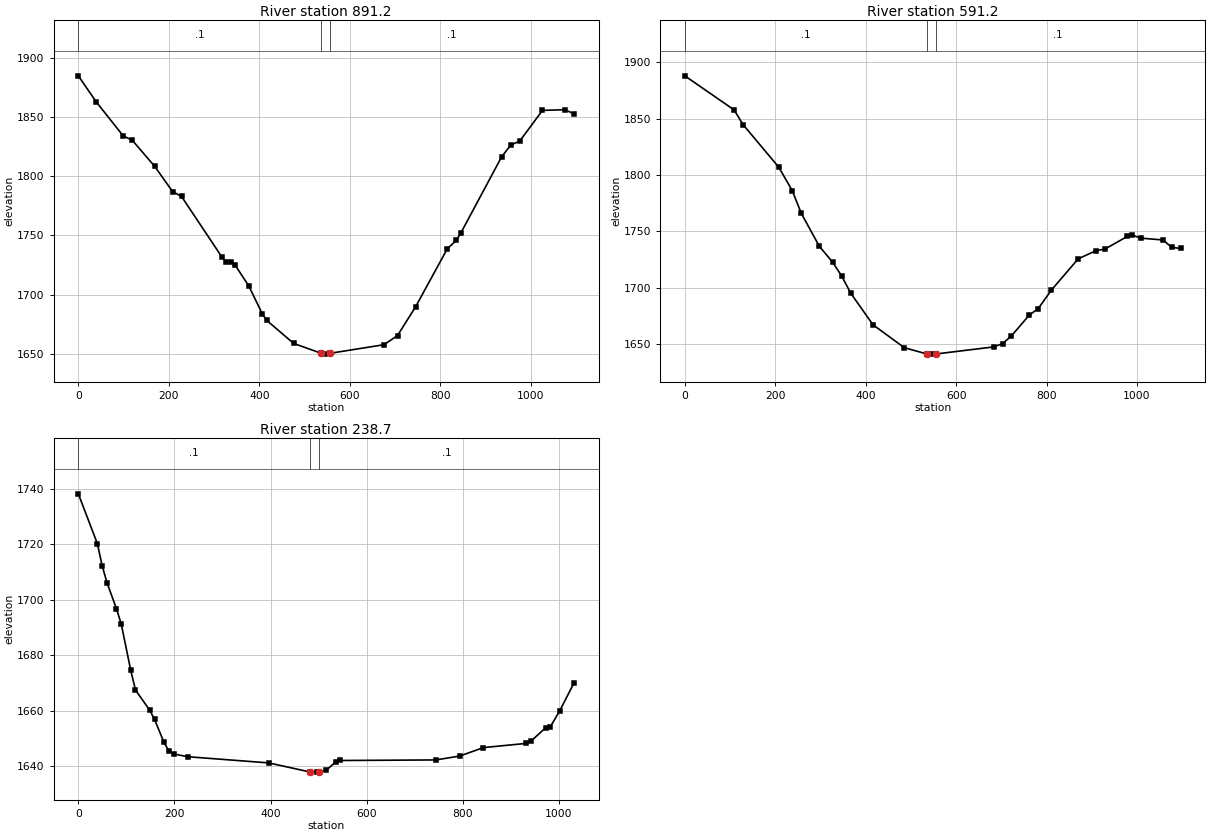
Type RM Length L Ch R = 1 ,891.2,298.6,300,294.8
XS GIS Cut Line= 3
     1878585.257      231715.304     1878258.141      232151.499
     1877875.365      232546.990
#Sta/Elev= 30
       0 1884.76    39.6 1862.72    99.1 1834.07   119.0 1830.45   168.5 1808.43
   208.2 1787.10   228.0 1782.94   317.2 1731.79   327.1 1727.72   337.0 1727.98
   347.0 1724.64   376.7 1707.36   406.4 1683.87   416.4 1678.26   475.8 1658.84
   535.2 1650.74   545.2 1649.82   555.2 1650.45   675.3 1657.77   705.3 1665.52
   745.4 1689.89   815.4 1738.84   835.4 1745.89   845.4 1752.22   935.5 1816.50
   955.5 1826.29   975.5 1829.74  1025.6 1855.59  1075.6 1856.16  1095.6 1852.53
#Mann= 3 , 0 , 0
       0     0.1       0   535.2   0.045       0   555.2     0.1       0
Bank Sta=   535.2,   555.2
Exp/Cntr=0.3,0.1

Type RM Length L Ch R = 1 ,591.2,367.8,352.5,340.7
XS GIS Cut Line= 3
     1878370.159      231551.726     1878020.067      231969.462
     1877727.073      232436.629
#Sta/Elev= 30
       0 1888.04   109.0 1857.82   128.8 1844.78   208.1 1806.81   237.8 1786.02
   257.6 1765.98   297.3 1736.94   327.0 1722.61   346.8 1710.54   366.7 1695.31
   416.2 1667.14   485.6 1646.78     535 1641.29   545.0 1641.10     555 1641.22
   682.9 1647.49   702.6 1650.40   722.3 1657.22   761.7 1675.71   781.4 1681.44
   810.9 1698.03   870.0 1725.65   909.4 1732.94   929.1 1734.29   978.3 1745.50
   988.2 1747.04  1007.9 1744.03  1057.1 1742.42  1076.8 1735.90  1096.5 1734.83
#Mann= 3 , 0 , 0
       0     0.1       0     535   0.045       0     555     0.1       0
Bank Sta=     535,     555
Exp/Cntr=0.3,0.1

Type RM Length L Ch R = 1 ,238.7,212.4,238.5,264.6
XS GIS Cut Line= 3
     1878096.097      231631.018     1877703.363      231796.439
     1877647.458      232399.580
#Sta/Elev= 30
       0 1738.29    39.6 1720.31    49.6 1712.31    59.5 1706.27    79.3 1696.82
    89.2 1691.38   109.0 1674.61   118.9 1667.47   148.7 1660.12   158.6 1656.82
   178.4 1648.51   188.3 1645.51   198.2 1644.36   227.9 1643.36   396.4 1641.13
   481.1 1637.89   495.7 1637.80   501.1 1637.80   515.5 1638.42   535.4 1641.44
   545.3 1642.00   743.9 1642.20   793.6 1643.60   843.2 1646.66   932.6 1648.18
   942.5 1649.06   972.3 1653.78   982.2 1654.14  1002.1 1660.01  1031.9 1670.13
#Mann= 3 , 0 , 0
       0     0.1       0   481.1   0.045       0   501.1     0.1       0
Bank Sta=   481.1,   501.1
Exp/Cntr=0.3,0.1